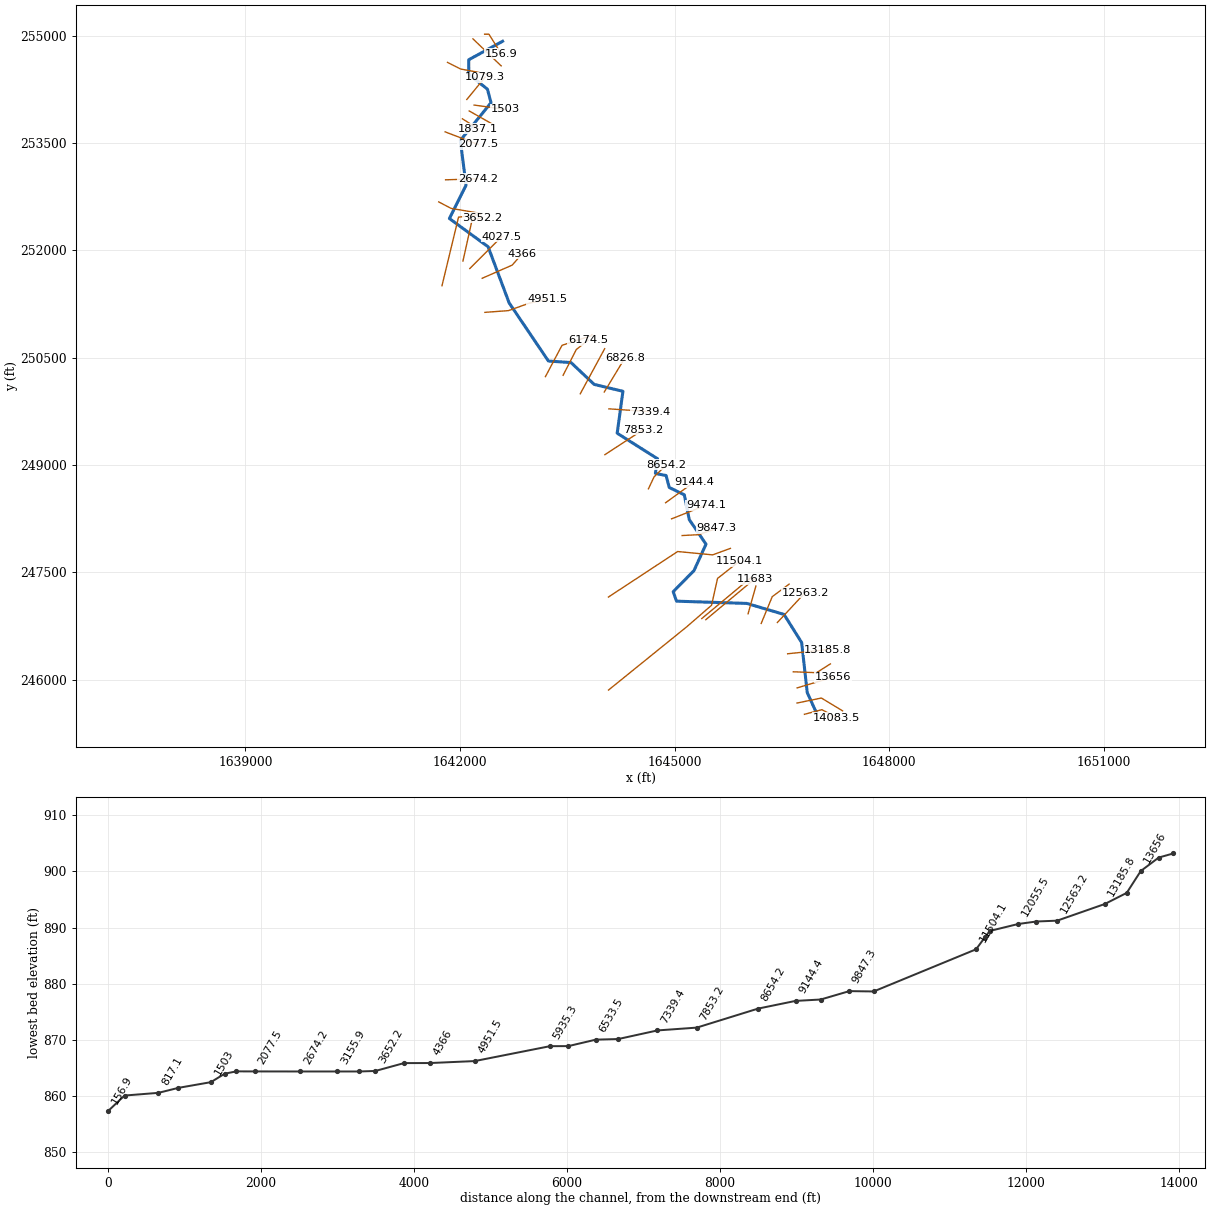
--- INDIANFRK.prj (project) ---

Proj Title=INDIANFRK
Current Plan=p01
Default Exp/Contr=0,0
English Units
Geom File=g01
Flow File=f01
Plan File=p01
BEGIN DESCRIPTION:
END DESCRIPTION:
DSS Export Rating Curves= 0
DSS Export Rating Curve Sorted= 0
DSS Export Volume Flow Curves= 0
DXF OffsetX= 0
DXF OffsetY= 0
DXF ScaleX= 0
DXF ScaleY= 0

--- INDIANFRK.p01 (plan) ---

Plan Title=Floodplain
Program Version=4.00
Geom File=g01
Flow File=f01
K Sum by GR=0
Std Step Tol=0.01
Critical Tol=0.01
Num of Std Step Trials=20
Max Error Tol=0.3
Flow Tol Ratio=0.001
Split Flow NTrial=30
Split Flow Tol=0.02
Split Flow Ratio=0.02
Log Output Level=0
Friction Slope Method=1
Unsteady Friction Slope Method=2
Unsteady Bridges Friction Slope Method=1
Global Log Level=0
CheckData=False
Run HTab=0
Run UNet=0
Run PostProcess=0
UNET Theta=0
UNET Theta Warmup=0
UNET ZTol=0
UNET ZSATol=0
UNET MxIter=0
UNET MaxInSteps=0
UNET DtIC=0
UNET DtMin=0
UNET MaxCRTS=0
UNET WFStab=0
UNET SFStab=0
UNET WFX=0
UNET SFX=0
UNET DSS MLevel=0
UNET DZMax Abort=0
UNET Convert EG Bridges=0
UNET Use Existing IB Tables=0
UNET Froude Limit=0
UNET Froude Power=0
Write IC File=0
Echo Input=False
Echo Output=False
Write Detailed=0

--- INDIANFRK.f01 (steady flow) ---

Flow Title=NFF Regression Equation
Program Version=4.10
Number of Profiles= 1
Profile Names=P100yr
River Rch & RM=INDIANFRK,Main            ,14083.5
 953.972
River Rch & RM=INDIANFRK,Main            ,12563.2
1049.443
River Rch & RM=INDIANFRK,Main            ,10165.3
1837.955
River Rch & RM=INDIANFRK,Main            ,4951.5
2013.236
River Rch & RM=INDIANFRK,Main            ,374.3
2232.626
River Rch & RM=INDIANFRK,Main            ,156.9
2234.292
Boundary for River Rch & Prof#=INDIANFRK,Main            , 1
Up Type= 0
Dn Type= 3
Dn Slope=0.01323
DSS Import GetInterval= 0
DSS Import GetPeak= 0
DSS Import FillOption= 0

--- INDIANFRK.g01 (geometry) ---

Geom Title=USGS 10m DEM
Program Version=4.10

River Reach=INDIANFRK       ,Main
Reach XY= 30
     1646978.072      245547.183     1646855.459      245817.365
     1646777.334      246517.235     1646531.023       246910.03
      1646010.19       247064.11     1645028.202      247095.577
     1644981.544      247227.955     1645272.343      247523.094
     1645439.829       247891.97     1645205.454      248237.022
     1645137.095      248582.074     1644926.591      248685.156
     1644882.103      248852.256     1644732.364      248881.553
     1644762.746      249086.631      1644198.51      249443.619
     1644278.805      250029.557     1643876.244      250126.128
     1643553.114      250431.178     1643237.138      250452.734
     1642688.093      251265.451     1642394.039      252049.956
      1641852.59      252444.921     1642085.879      252911.501
     1642005.584      253536.501     1642434.801      254064.395
     1642384.454      254253.631     1642123.531      254461.574
     1642122.662      254664.265     1642596.534      254922.946

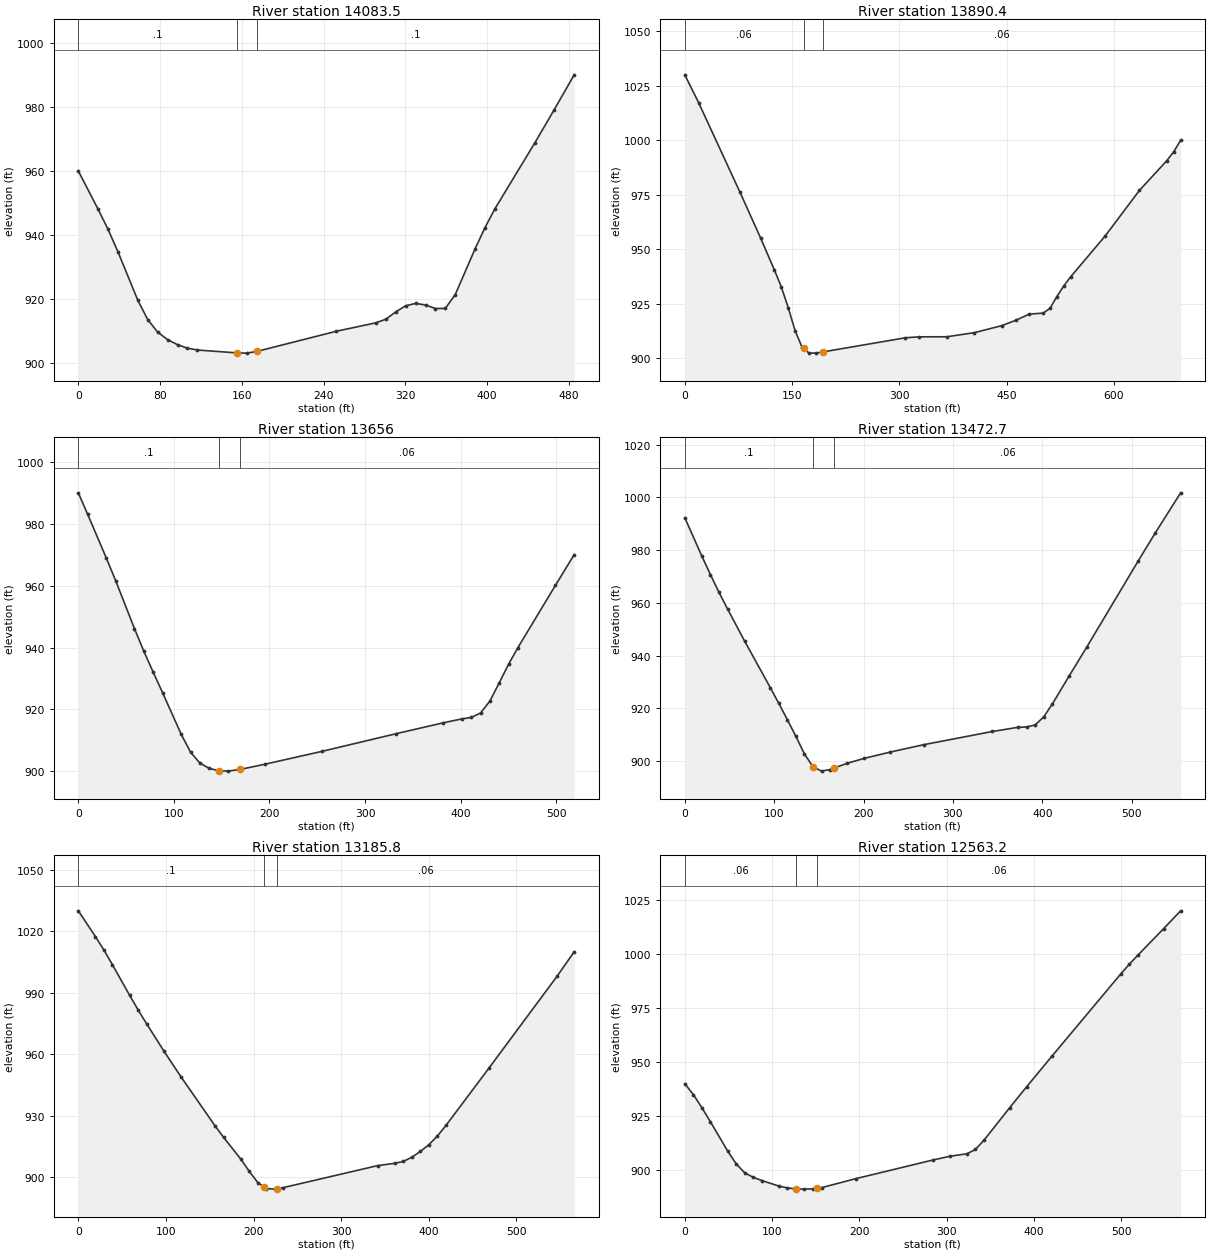
Type RM Length L Ch R = 1 ,14083.5 ,193.9,193.1,191.8
XS GIS Cut Line= 3
     1646815.959      245513.986      1647060.04      245578.778
     1647265.442      245469.223
#Sta/Elev= 30
       0     960    19.4  948.04    29.1  941.78    38.8  934.78    58.3  919.61
      68  913.61    77.7  909.72    87.4  907.38    97.1  905.81   106.8  904.72
   116.6  904.15   155.5  903.25   165.1  903.18   174.8  903.72   252.5     910
   291.3  912.64     301  913.77   310.7  916.03   320.4  917.96   330.1  918.68
   339.8  918.21   349.5  917.09   359.2  917.14   368.9  921.44   388.3  935.69
     398  942.32   407.7  948.19   446.5  968.61   465.9  979.18   485.3     990
#Mann= 3 , 0 , 0
       0      .1       0   155.5    .045       0   174.8      .1       0
Bank Sta=155.5,174.8
XS Rating Curve= 0 ,0
Exp/Cntr=0.3,0.1

Type RM Length L Ch R = 1 ,13890.4 ,232.6,234.4,235.7
XS GIS Cut Line= 3
     1646713.176      245671.465     1647053.284       245741.38
     1647349.575      245562.376
#Sta/Elev= 30
       0    1030    19.3 1017.26    77.2  976.18   106.1  955.13   125.4  940.47
     135  932.76   144.7  923.25   154.3  912.65     164  905.18   166.1  904.59
   173.6   902.5   183.3  902.44   192.9  902.98   308.6  909.48   327.9   909.9
   366.4  909.94   404.9  911.82   443.4  915.05   462.6  917.45   481.8  920.33
   501.1  920.78   510.7  922.95   520.3  928.37   529.9  933.18   539.5  937.37
   587.6  956.02   635.7  976.99   674.2   990.7   683.8  994.79   693.4    1000
#Mann= 3 , 0 , 0
       0     .06       0   166.1    .045       0   192.9     .06       0
Bank Sta=166.1,192.9
XS Rating Curve= 0 ,0
Exp/Cntr=0.3,0.1

Type RM Length L Ch R = 1 ,13656   ,190.8,183.3,176
XS GIS Cut Line= 2
     1646714.681      245883.135     1647211.781      246031.492
#Sta/Elev= 28
       0     990     9.8  983.03    29.4  968.85    39.2  961.49    58.7  946.14
    68.5  938.82    78.3  932.04    88.1  925.44   107.7   911.9   117.5  906.14
   127.2  902.63     137  900.93   146.8  900.16   156.6  900.04   169.3  900.59
   195.8  902.31   254.5   906.4   332.8  912.16   381.7  915.65   401.3  916.92
   411.1   917.4   420.9  918.83   430.7  922.73   440.5  928.65   450.2  934.61
     460  939.99   499.2  960.09   518.8     970
#Mann= 3 , 0 , 0
       0      .1       0   146.8    .045       0   169.3     .06       0
Bank Sta=146.8,169.3
XS Rating Curve= 0 ,0
Exp/Cntr=0.3,0.1

Type RM Length L Ch R = 1 ,13472.7 ,283.5,286.9,290.2
XS GIS Cut Line= 3
     1646660.607      246108.383     1646985.406      246095.689
     1647179.193      246219.006
#Sta/Elev= 30
       0  992.29    19.1  977.71    28.7   970.7    38.2  964.02    47.8   957.7
    66.9  945.51    95.6  927.86   105.2  921.82   114.7  915.71   124.3  909.33
   133.8  902.73   143.4  897.78     153  896.16   162.5  896.77   167.1  897.34
   181.6  899.13   200.8     901   229.4  903.36   267.7  906.22   344.2   911.2
   372.9  912.78   382.5  912.92     392  913.68   401.6  916.76   411.2  921.63
   430.3  932.43   449.5   943.1   506.9  975.69     526  986.33   554.7 1001.73
#Mann= 3 , 0 , 0
       0      .1       0   143.4    .045       0   167.1     .06       0
Bank Sta=143.4,167.1
XS Rating Curve= 0 ,0
Exp/Cntr=0.3,0.1

Type RM Length L Ch R = 1 ,13185.8 ,581.9,622.6,630
XS GIS Cut Line= 2
     1646581.549      246360.114     1647144.493      246419.487
#Sta/Elev= 30
       0    1030    19.5 1017.46    29.3  1010.8      39 1003.65    58.6  988.75
    68.3  981.61    78.1  974.78    97.6  961.62   117.1  949.05   156.2  925.01
   165.9  919.41   185.4  908.88   195.2  902.85     205  897.33   211.6  895.39
   214.7  894.48   224.5  894.18   226.6  894.34   234.2  894.94   341.6  905.64
   361.1  906.77   370.9  907.68   380.6  909.71   390.4  912.55   400.2  915.85
   409.9  920.07   419.7  925.24   468.5  953.06   546.6  998.08   566.1    1010
#Mann= 3 , 0 , 0
       0      .1       0   211.6    .045       0   226.6     .06       0
Bank Sta=211.6,226.6
XS Rating Curve= 0 ,0
Exp/Cntr=0.3,0.1

Type RM Length L Ch R = 1 ,12563.2 ,290,271,279.3
XS GIS Cut Line= 2
     1646437.575      246796.841     1646824.126       247212.92
#Sta/Elev= 30
       0  940.03     9.8  934.98    19.6  928.91    29.4  922.33      49  908.91
    58.8  902.93    68.5  898.81    78.3  896.69    88.1  895.21   107.7  892.64
   117.5  891.78   127.3  891.32   136.8  891.22   146.9  891.36   151.8  891.64
   156.7  891.91   195.8  896.06     284  904.68   303.6  906.43   323.1  907.57
   332.9  909.58   342.7  913.87   372.1  928.89   391.7  938.67     421  952.99
   499.4  990.82   509.2  995.32     519   999.5   548.4 1011.74   567.9    1020
#Mann= 3 , 0 , 0
       0     .06       0   127.3    .045       0   151.8     .06       0
Bank Sta=127.3,151.8
XS Rating Curve= 0 ,0
Exp/Cntr=0.3,0.1

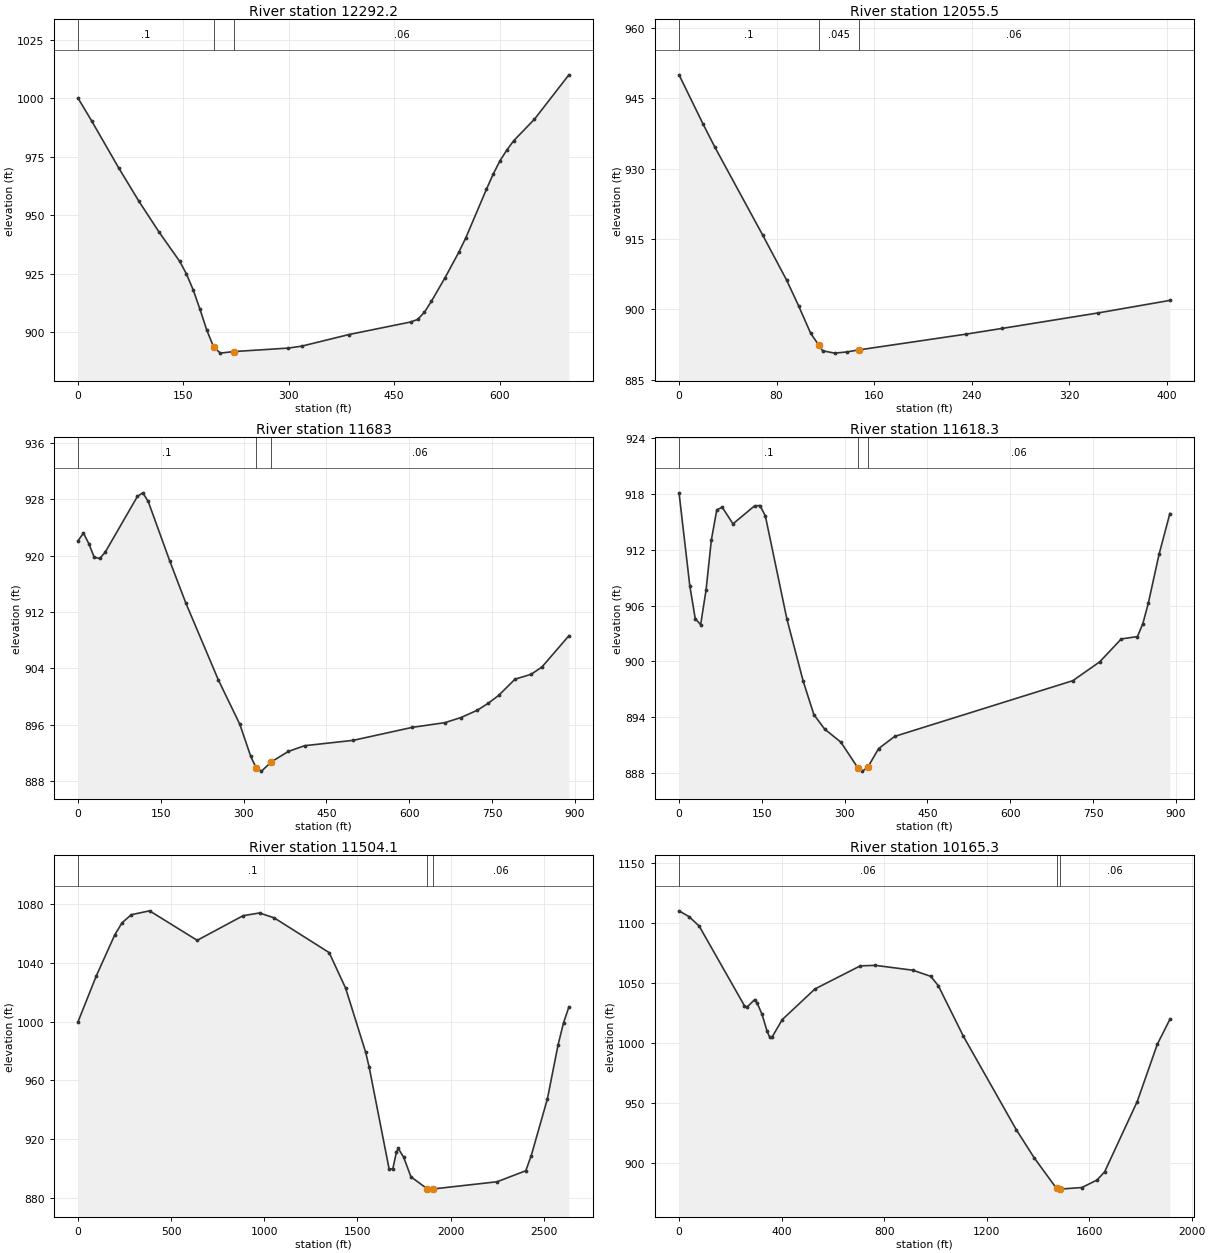
Type RM Length L Ch R = 1 ,12292.2 ,234.1,236.7,239.4
XS GIS Cut Line= 3
     1646211.834      246783.656     1646365.819      247158.151
     1646601.553      247333.664
#Sta/Elev= 30
       0    1000    19.3  990.32    57.8  970.24    86.8  955.88   115.7  942.62
   144.6  930.32   154.2  924.96   163.9  918.08   173.5  909.85   183.2  900.94
   192.9  893.76   202.5  891.07   221.7  891.74   298.9  893.22   318.2  894.04
   385.6  899.01   473.5  904.38   483.3  905.45   493.1  908.54   502.9  913.17
   522.5  923.32   542.1  934.21   551.9  940.26   581.3  961.04     591  967.56
   600.8  973.35   610.6  977.92   620.4  981.91   649.8  991.04   698.8    1010
#Mann= 3 , 0 , 0
       0      .1       0   192.9    .045       0   221.7     .06       0
Bank Sta=192.9,221.7
XS Rating Curve= 0 ,0
Exp/Cntr=0.3,0.1

Type RM Length L Ch R = 1 ,12055.5 ,389.9,372.5,344.2
XS GIS Cut Line= 2
     1646028.328      246919.084     1646137.353      247306.701
#Sta/Elev= 16
       0     950    19.6  939.56    29.5  934.52    68.8  915.73    88.4  906.14
    98.2  900.66     108  894.86   114.6  892.35   117.8  891.13   127.7  890.63
   137.5  890.88   147.3  891.31   235.7  894.69   265.2  895.91   343.7   899.2
   402.7  901.88
#Mann= 3 , 0 , 0
       0      .1       0   114.6    .045       0   147.3     .06       0
Bank Sta=114.6,147.3
XS Rating Curve= 0 ,0
Exp/Cntr=0.3,0.1

Type RM Length L Ch R = 1 ,11683   ,66.4,64.7,75.9
XS GIS Cut Line= 2
     1645436.889      246836.181     1646119.793      247405.808
#Sta/Elev= 30
       0  922.11     9.8  923.18    19.5  921.68    29.3  919.74    39.1  919.58
    48.9  920.44   107.5  928.39   117.3   928.9     127  927.69   166.1  919.23
   195.4  913.22   254.1  902.35   293.2  896.01   312.7  891.51   322.5  889.88
   332.3  889.39   350.4  890.72   381.1  892.19   410.4     893   498.4  893.76
   605.9  895.61   664.5  896.27   693.8     897   723.2  898.03   742.7     899
   762.2  900.15   791.6  902.44   820.9  903.14   840.4  904.17   889.3  908.61
#Mann= 3 , 0 , 0
       0      .1       0   322.5    .045       0   350.4     .06       0
Bank Sta=322.5,350.4
XS Rating Curve= 0 ,0
Exp/Cntr=0.3,0.1

Type RM Length L Ch R = 1 ,11618.3 ,97,114.2,131.9
XS GIS Cut Line= 2
     1645381.866      246852.978     1646064.769      247422.605
#Sta/Elev= 30
       0  918.09    19.5  908.12    29.3  904.61    39.1  903.94    48.9  907.64
    58.6  913.05    68.4  916.26    78.2  916.55    97.7  914.76   136.8  916.69
   146.6  916.73   156.4  915.61   195.4  904.56   224.8  897.92   244.3   894.3
   263.8  892.75   293.2  891.35   323.9   888.6   332.3  888.24     342  888.66
   361.6  890.66   390.9  891.97   713.4  897.94   762.2  899.96   801.3  902.42
   830.6  902.67   840.4  904.07   850.2  906.24   869.7  911.49   889.3  915.87
#Mann= 3 , 0 , 0
       0      .1       0   323.9    .045       0     342     .06       0
Bank Sta=323.9,342
XS Rating Curve= 0 ,0
Exp/Cntr=0.3,0.1

Type RM Length L Ch R = 1 ,11504.1 ,1369.3,1338.9,1305
XS GIS Cut Line= 5
     1644077.498      245853.029     1645171.801      246737.993
     1645517.885      247038.421     1645601.401      247413.472
     1645904.823      247651.868
#Sta/Elev= 30
       0    1000    98.4 1031.26   196.8 1058.91   236.2 1067.21   285.4 1072.65
   383.8 1075.31   639.7 1055.26   885.8 1071.99   974.3 1073.86  1053.1 1070.54
  1348.3 1046.91  1436.6 1022.79  1543.9  979.38  1563.4  968.91  1670.6  899.66
  1690.1  899.93  1709.6  911.28  1719.4  913.82  1748.6  907.76  1787.6   894.5
  1875.3  886.32  1884.9  886.13  1904.1  886.22  2249.9  891.13  2404.2  898.63
  2433.2  908.77    2520   947.3  2577.9   984.3  2606.8  999.16  2635.8    1010
#Mann= 3 , 0 , 0
       0      .1       0  1875.3    .045       0  1904.1     .06       0
Bank Sta=1875.3,1904.1
XS Rating Curve= 0 ,0
Exp/Cntr=0.3,0.1

Type RM Length L Ch R = 1 ,10165.3 ,308.1,318,326.9
XS GIS Cut Line= 4
     1644075.793      247153.055     1645043.738      247789.566
     1645533.277      247742.915     1645781.623      247833.782
#Sta/Elev= 30
       0 1110.42    39.3 1105.54    78.5 1097.75   255.3  1031.3   265.1 1030.27
   294.5 1036.36   304.4 1033.84     324 1024.08   343.6 1010.04   353.4 1005.31
   363.2 1005.38   402.5 1019.81   530.2 1045.34   706.9 1064.57   765.8 1065.01
     913 1060.92   981.8 1055.84  1011.2 1048.14  1109.4 1005.88  1315.8  928.05
  1384.7  904.97  1472.7  879.17    1483  878.63  1487.7  878.68  1571.6  879.97
  1630.6  886.22    1660  892.94  1787.4   951.6  1865.7  999.24  1914.7 1020.01
#Mann= 3 , 0 , 0
       0     .06       0  1472.7    .045       0  1487.7     .06       0
Bank Sta=1472.7,1487.7
XS Rating Curve= 0 ,0
Exp/Cntr=0.3,0.1

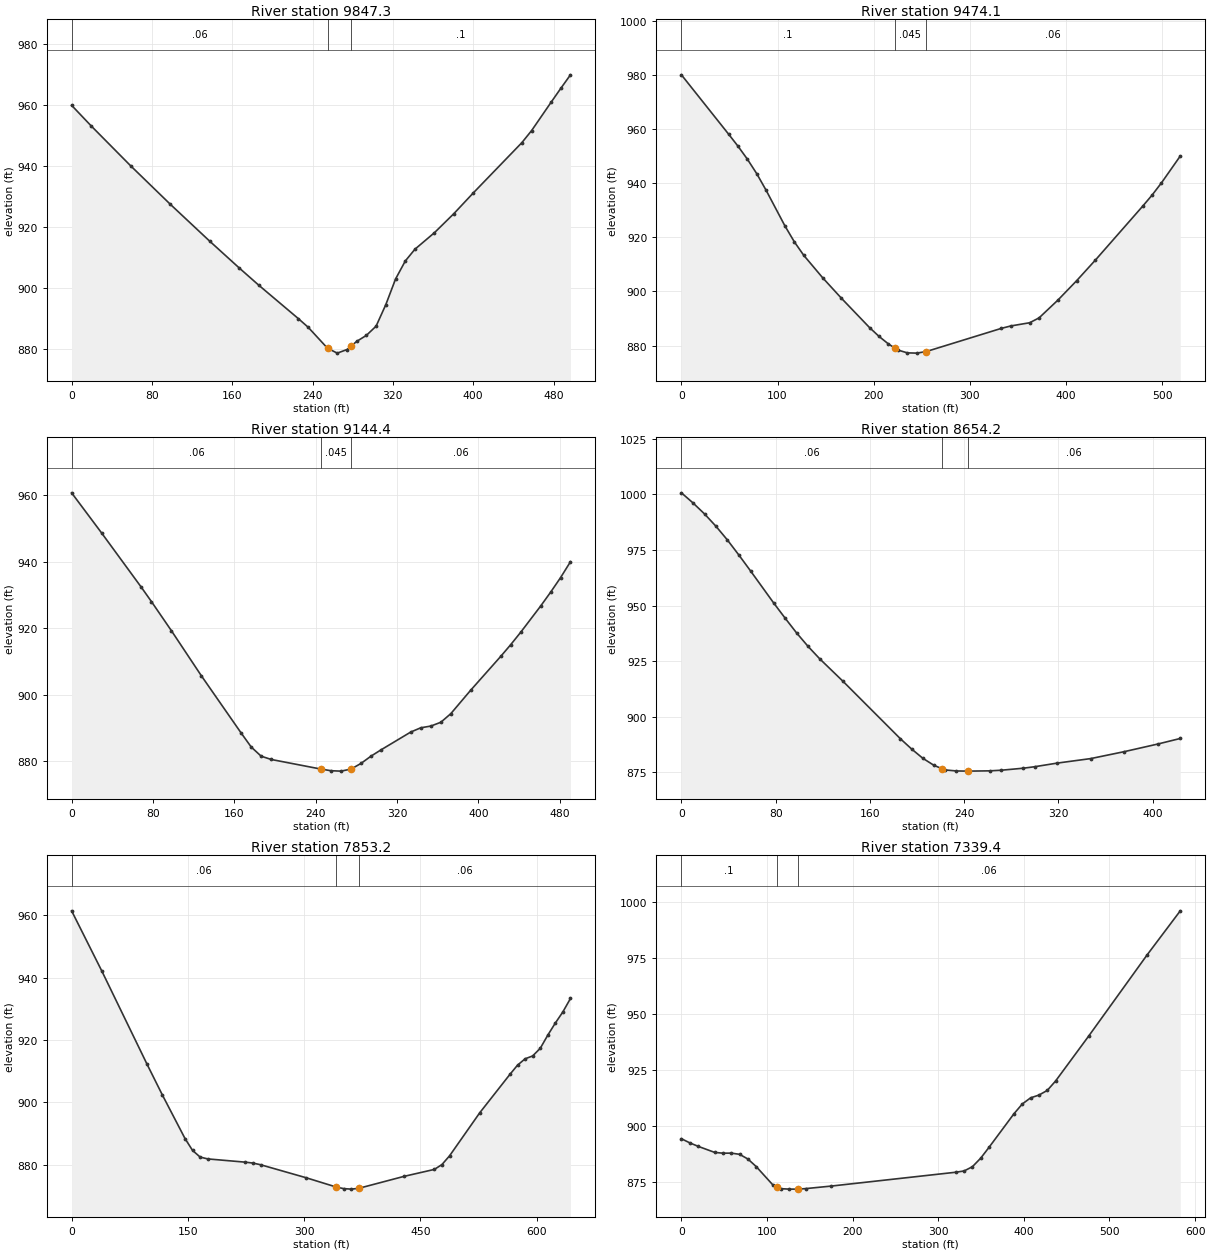
Type RM Length L Ch R = 1 ,9847.3  ,372.3,373.2,373.5
XS GIS Cut Line= 3
     1645106.283       248013.18     1645331.883      248024.647
     1645588.326       248112.38
#Sta/Elev= 28
       0     960    19.6   953.2    58.9  940.12    98.2  927.56   137.5  915.44
     167  906.62   186.6  900.93   225.9     890   235.6  887.19   254.9   880.3
   264.6  878.69   274.3  879.86   278.5  881.02     284  882.55   293.6  884.51
   303.3  887.54     313  894.62   322.7  903.03   332.4  908.93     342  912.79
   361.4   918.2   380.8  924.47   400.1  931.25   448.5  947.75   458.2  951.71
   477.6     961   487.2  965.53   496.9     970
#Mann= 3 , 0 , 0
       0     .06       0   254.9    .045       0   278.5      .1       0
Bank Sta=254.9,278.5
XS Rating Curve= 0 ,0
Exp/Cntr=0.3,0.1

Type RM Length L Ch R = 1 ,9474.1  ,324.4,329.6,335.4
XS GIS Cut Line= 2
     1644957.872      248246.192     1645440.555      248436.773
#Sta/Elev= 30
       0     980      49  958.13    58.8  953.67    68.5  948.91    78.3  943.53
    88.1  937.37   107.7  924.19   117.5   918.3   127.3  913.32   146.9  905.06
   166.4   897.5   195.8  886.61   205.6  883.38   215.4  880.58   221.9   879.1
   225.2  878.35     235   877.3   244.8   877.2   254.6  877.77   332.9  886.35
   342.7  887.24   362.3  888.42   372.1  890.22   391.7  896.79   411.2  903.96
   430.8  911.61   479.8  931.44   489.6  935.54   499.4  940.08     519     950
#Mann= 3 , 0 , 0
       0      .1       0   221.9    .045       0   254.6     .06       0
Bank Sta=221.9,254.6
XS Rating Curve= 0 ,0
Exp/Cntr=0.3,0.1

Type RM Length L Ch R = 1 ,9144.4  ,486.2,490.2,492
XS GIS Cut Line= 2
     1644875.272      248471.631     1645272.829      248759.182
#Sta/Elev= 30
       0  960.74    29.4   948.7    68.7  932.25    78.5     928    98.1  919.25
   127.6  905.66   166.8   888.4   176.6  884.22   186.4  881.45   196.3  880.46
   245.3  877.56   255.1  877.07     265  876.95   274.8  877.57   284.6  879.27
   294.4  881.45   304.2  883.34   333.6  888.73   343.4     890   353.3  890.52
   363.1  891.66   372.9  894.24   392.5  901.32     422  911.49   431.8  915.01
   441.6  918.74   461.2  926.62     471  930.79   480.8  935.18   490.6     940
#Mann= 3 , 0 , 0
       0     .06       0   245.3    .045       0   274.8     .06       0
Bank Sta=245.3,274.8
XS Rating Curve= 0 ,0
Exp/Cntr=0.3,0.1

Type RM Length L Ch R = 1 ,8654.2  ,805.5,801.1,796.9
XS GIS Cut Line= 3
      1644635.57      248666.897     1644715.116      248834.913
     1644885.689      249000.277
#Sta/Elev= 30
       0 1000.67     9.8  996.15    19.6   991.2    29.4   985.6    39.1  979.44
    48.9  972.63    58.7  965.57    78.3  951.18    88.1   944.3    97.8  937.69
   107.6   931.6   117.4  926.07     137  916.05   185.9  890.14   195.4  885.54
   204.9  881.37   214.4  878.18   221.4  876.65   223.9  876.11   233.4  875.66
   242.9  875.58   261.9  875.71   271.4  875.98   290.4   876.9   299.9  877.56
   318.9  879.18   347.4  881.21     376  884.34   404.5  887.77   423.5  890.26
#Mann= 3 , 0 , 0
       0     .06       0   221.4    .045       0   242.9     .06       0
Bank Sta=221.4,242.9
XS Rating Curve= 0 ,0
Exp/Cntr=0.3,0.1

Type RM Length L Ch R = 1 ,7853.2  ,528.4,513.8,498.9
XS GIS Cut Line= 2
     1644026.195      249143.459     1644565.257      249495.022
#Sta/Elev= 30
       0  961.41      39   942.1    97.5  912.15     117  902.43   146.3  888.42
     156  884.62   165.8  882.48   175.5  881.89   224.3  880.84     234  880.55
   243.8  880.02   302.3  875.87   341.3  872.88     351  872.36   360.8   872.2
   370.5  872.46     429   876.3     468  878.52   477.8  880.08   487.6  882.87
   526.6  896.69   565.6  909.02   575.3  911.94   585.1  913.98   594.8  914.89
   604.6  917.33   614.3  921.54   624.1  925.45   633.8  929.01   643.6  933.32
#Mann= 3 , 0 , 0
       0     .06       0   341.3    .045       0   370.5     .06       0
Bank Sta=341.3,370.5
XS Rating Curve= 0 ,0
Exp/Cntr=0.3,0.1

Type RM Length L Ch R = 1 ,7339.4  ,487.3,512.6,538
XS GIS Cut Line= 2
     1644082.839       249784.11     1644664.215      249745.022
#Sta/Elev= 30
       0  894.25     9.7  892.42    19.4  890.87    38.8  888.14    48.6  887.78
    58.3  887.81      68  887.27    77.7  885.16    87.4  881.78   106.8  873.59
   111.5  872.77   116.5  871.89   126.2   871.7     136   871.7   145.7  871.95
   174.8  873.06   320.5  879.26   330.2  879.83   339.9  881.73   349.6  885.56
   359.3   890.4   388.5  905.46   398.2  909.81   407.9  912.55   417.6  913.78
   427.3  915.86     437  920.05   475.9  940.28   543.8  976.42   582.7  996.23
#Mann= 3 , 0 , 0
       0      .1       0   111.5    .045       0     136     .06       0
Bank Sta=111.5,136
XS Rating Curve= 0 ,0
Exp/Cntr=0.3,0.1

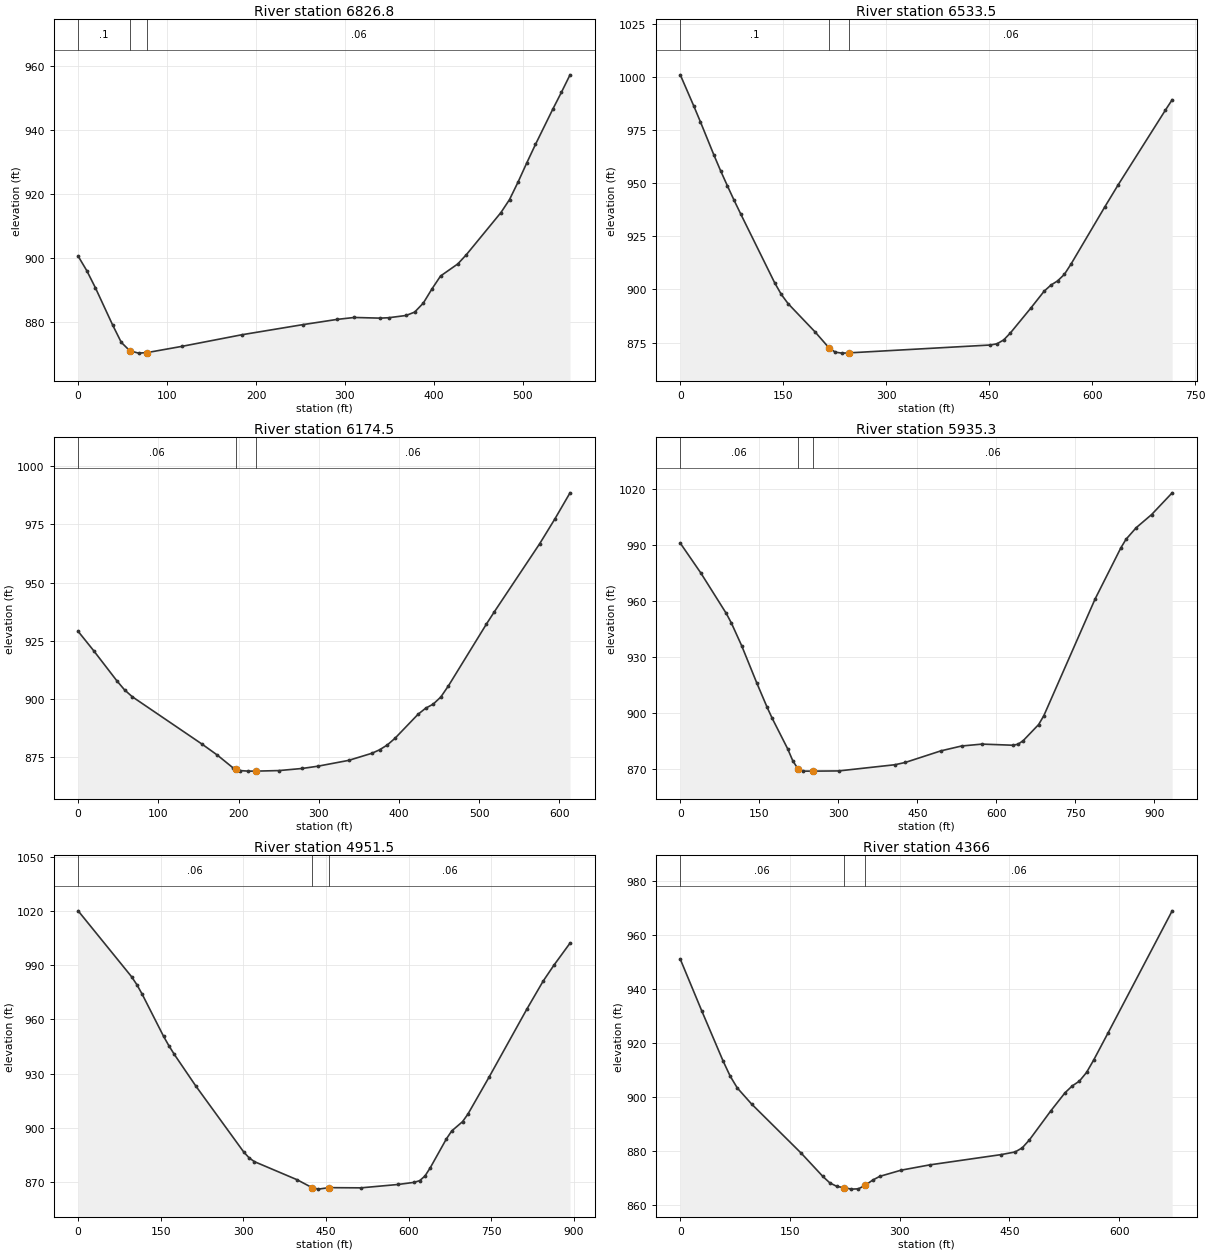
Type RM Length L Ch R = 1 ,6826.8  ,291.8,293.3,294
XS GIS Cut Line= 2
     1644017.518       250018.94     1644303.976      250492.031
#Sta/Elev= 30
       0   900.5     9.7  895.96    19.4  890.61    38.8  878.96    48.5  873.54
    58.1  870.91    67.9  870.17    77.6  870.34   116.4  872.27   184.4  875.93
   252.3  879.06   291.1  880.71   310.5  881.32   339.6  881.11   349.3  881.24
   368.7  881.94   378.4     883   388.1  885.81   397.8  890.23   407.5  894.28
   426.9  898.06   436.6  900.97   475.4  914.12   485.1   918.2   494.8  923.74
   504.5  929.67   514.2   935.4   533.6  946.38   543.4  951.71   553.1  957.18
#Mann= 3 , 0 , 0
       0      .1       0    58.1    .045       0    77.6     .06       0
Bank Sta=58.1,77.6
XS Rating Curve= 0 ,0
Exp/Cntr=0.3,0.1

Type RM Length L Ch R = 1 ,6533.5  ,358.5,359.1,359.5
XS GIS Cut Line= 2
     1643682.445      249995.022      1644023.59       250625.23
#Sta/Elev= 30
       0 1000.89    19.6   986.3    29.4  978.75    49.1  963.11    58.9  955.69
    68.7  948.66    78.5  941.85    88.4  935.25   137.4   903.2   147.2  897.64
   157.1  893.32   196.3  880.06   216.6  872.57   225.8  870.51   235.6  870.06
   245.4  870.17   451.6  873.88   461.4  874.45   471.2  876.27     481  879.58
   510.5  891.17   530.1  899.18   539.9  902.03   549.7  904.02   559.6   907.1
   569.4  912.01   618.4  938.78   638.1  949.27   706.8  984.33   716.6  989.18
#Mann= 3 , 0 , 0
       0      .1       0   216.6    .045       0   245.4     .06       0
Bank Sta=216.6,245.4
XS Rating Curve= 0 ,0
Exp/Cntr=0.3,0.1

Type RM Length L Ch R = 1 ,6174.5  ,239.7,239.2,238.3
XS GIS Cut Line= 3
     1643442.431      250253.315     1643626.893      250613.559
     1643789.653      250743.767
#Sta/Elev= 30
       0  929.04    19.3  920.75    48.2  907.79    57.8  903.89    67.4  900.93
   154.2  880.59   173.4  875.84   192.7  870.43   197.4   869.8   202.4  869.13
     212  868.91   221.6  868.91   250.5  869.15   279.4  870.06   298.7  871.02
   337.3  873.54   366.2  876.59   375.8  878.09   385.4  880.16   395.1  883.07
   423.7  893.35   433.2  895.97   442.6  897.72   452.1  900.79   461.6  905.59
   508.9  932.13   518.4  937.22   575.3   966.7   594.2  977.33   613.2  988.62
#Mann= 3 , 0 , 0
       0     .06       0   197.4    .045       0   221.6     .06       0
Bank Sta=197.4,221.6
XS Rating Curve= 0 ,0
Exp/Cntr=0.3,0.1

Type RM Length L Ch R = 1 ,5935.3  ,1000.8,983.8,966.8
XS GIS Cut Line= 3
     1643195.465      250234.605     1643427.236      250672.105
     1643843.903      250810.126
#Sta/Elev= 30
       0  991.05    38.8  975.15    87.4  953.36    97.1   948.2   116.5  936.14
   145.6   915.9     165  903.04   174.7   897.1   203.9  880.87   213.6  874.47
   223.3  870.19     233   868.9   252.4   868.9   300.9  869.01   407.7  872.33
   427.2  873.55   495.1  879.78   534.1  882.36   573.1  883.38   631.7  882.77
   641.4  883.33   651.2  885.25   680.4  893.85   690.2  898.54   787.7  961.16
   836.5  988.48   846.2  993.06   865.8  999.35     895 1006.37     934    1018
#Mann= 3 , 0 , 0
       0     .06       0   223.3    .045       0   252.4     .06       0
Bank Sta=223.3,252.4
XS Rating Curve= 0 ,0
Exp/Cntr=0.3,0.1

Type RM Length L Ch R = 1 ,4951.5  ,583.1,585.5,587.5
XS GIS Cut Line= 4
     1642349.636        251133.1     1642678.266      251157.513
     1642969.771      251261.515     1643218.035      251313.598
#Sta/Elev= 30
       0    1020    96.9  983.63   106.6   979.2   116.3   973.9   155.1  950.64
   164.8  945.43   174.5  940.71   213.2  923.38   300.5  886.77   310.2  883.57
   319.8  881.45   397.2  871.46   424.7  867.05   435.9  866.25   455.3  867.07
   513.3  866.96     581  868.83     610  870.01   619.7  870.92   629.4  873.48
     639  878.04   668.3  894.01   678.1  898.43   697.6  903.52   707.3  907.66
   746.4  928.47   814.6  965.84   843.9  981.17   863.4  989.94   892.7 1002.16
#Mann= 3 , 0 , 0
       0     .06       0   424.7    .045       0   455.3     .06       0
Bank Sta=424.7,455.3
XS Rating Curve= 0 ,0
Exp/Cntr=0.3,0.1

Type RM Length L Ch R = 1 ,4366    ,330.2,338.5,346.9
XS GIS Cut Line= 3
     1642311.785      251609.779     1642730.929      251793.854
     1642872.549      251955.265
#Sta/Elev= 30
       0  951.13    29.2  932.07    58.4  913.47    68.2  907.79    77.9  903.41
    97.4  897.47   165.6  879.15   194.8  870.64   204.5   868.2   214.3  866.88
     224  866.44   233.8   865.9   243.5  866.01   253.2  867.39     263  869.24
   272.7  870.63   301.9  872.92   340.9  874.88   438.3  878.68   457.8  879.67
   467.5   881.2   477.3  884.14   506.6  894.92   526.1  901.64   535.9  904.16
   545.6  905.92   555.4  909.13   565.2  913.75   584.7  923.72   672.5  969.04
#Mann= 3 , 0 , 0
       0     .06       0     224    .045       0   253.2     .06       0
Bank Sta=224,253.2
XS Rating Curve= 0 ,0
Exp/Cntr=0.3,0.1

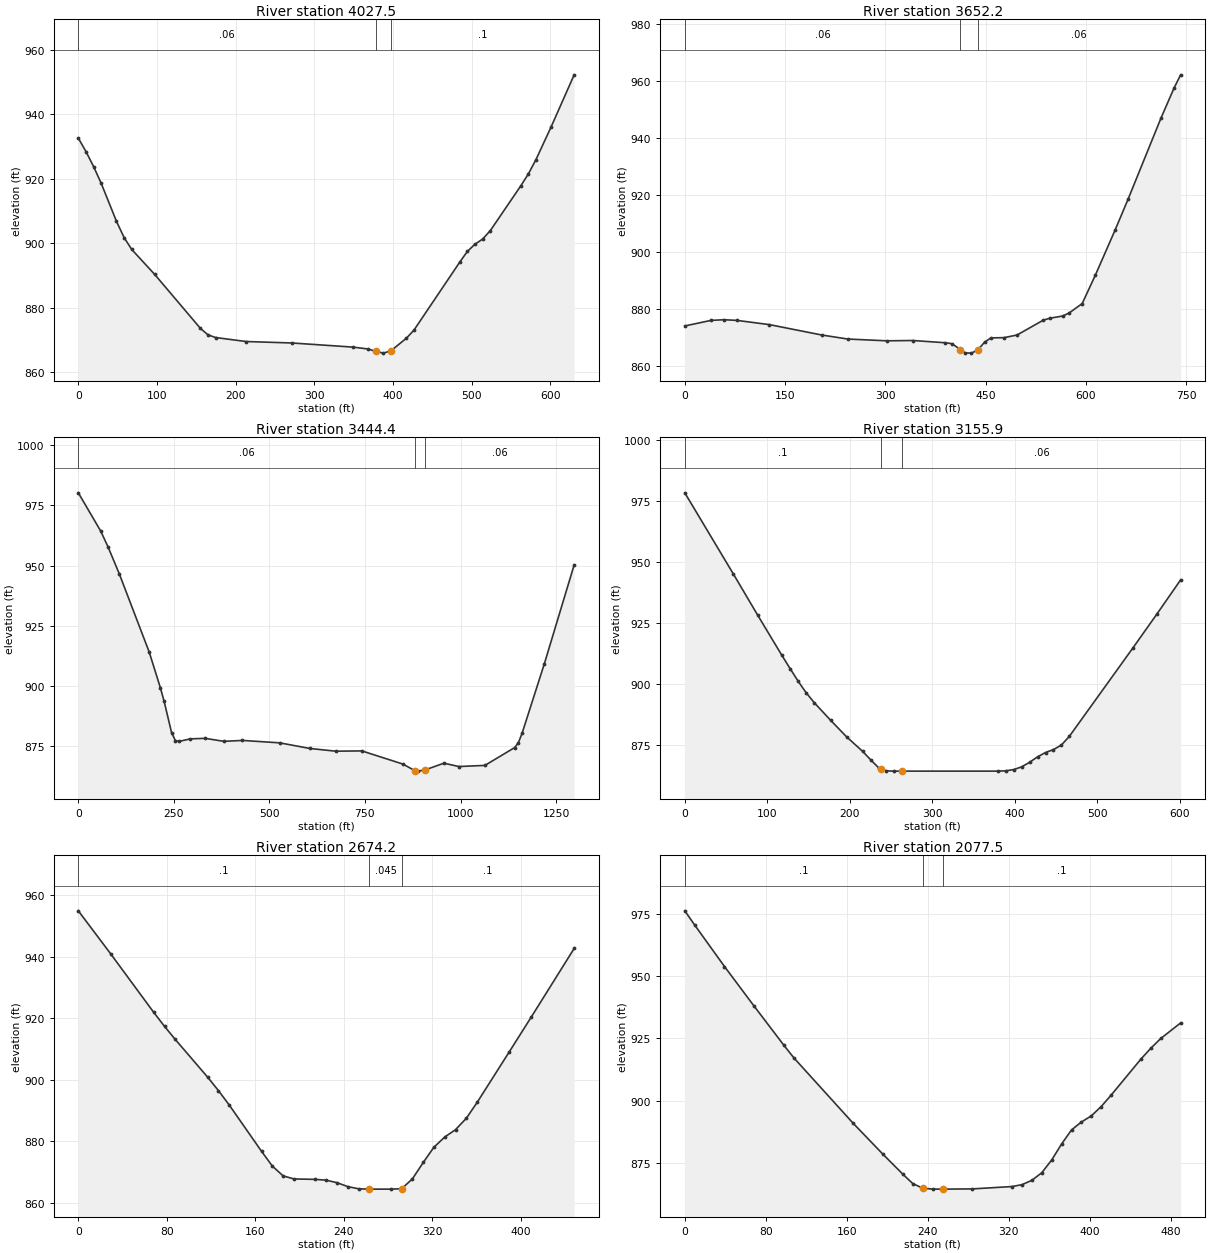
Type RM Length L Ch R = 1 ,4027.5  ,362.2,375.3,388
XS GIS Cut Line= 2
     1642138.177      251746.371     1642584.354      252191.376
#Sta/Elev= 30
       0  932.61     9.7  928.45    19.4  923.79    29.1  918.57    48.5  906.78
    58.2  901.74    67.9  898.06      97  890.33   155.1  873.59   164.8  871.56
   174.5  870.73   213.3  869.49   271.4  869.04     349  867.76   368.4  867.17
   378.1  866.43   387.8  865.89   397.5  866.65   416.9   870.5   426.6  873.03
   484.7   894.1   494.4  897.44   504.1  899.68   513.8  901.28   523.5  903.86
   562.3  917.78     572  921.51   581.7  925.97   601.1   936.2   630.2  952.26
#Mann= 3 , 0 , 0
       0     .06       0   378.1    .045       0   397.5      .1       0
Bank Sta=378.1,397.5
XS Rating Curve= 0 ,0
Exp/Cntr=0.3,0.1

Type RM Length L Ch R = 1 ,3652.2  ,208.4,207.8,207.6
XS GIS Cut Line= 3
     1642042.471      251850.881     1642171.594      252431.393
     1642316.993      252455.265
#Sta/Elev= 30
       0  874.02      39  875.97    58.5  876.21      78  875.98   126.7  874.49
   204.7  870.86   243.7  869.44   302.2  868.81   341.2  868.92     390  868.13
   399.7  867.81   412.4  865.76   419.2  864.58     429  864.49   438.7  865.66
   448.5  868.31   458.2  869.84   477.7  869.92   497.2  870.85   536.2  876.02
     546  876.73   565.4  877.51   575.2  878.58   594.7  881.89   614.4  891.86
   643.8   907.6   663.5  918.59   712.6  946.97   732.2  957.54     742  962.16
#Mann= 3 , 0 , 0
       0     .06       0   412.4    .045       0   438.7     .06       0
Bank Sta=412.4,438.7
XS Rating Curve= 0 ,0
Exp/Cntr=0.3,0.1

Type RM Length L Ch R = 1 ,3444.4  ,322.9,288.5,254.5
XS GIS Cut Line= 3
     1641749.285      251505.612     1641980.622      252463.946
     1642289.866      252501.923
#Sta/Elev= 30
       0  980.26    58.6  964.32    78.1  957.62   107.4  946.44   185.5  913.96
   214.7  899.08   224.5  893.46     244  880.42   253.8  877.14   263.6  876.77
   292.8  877.83   331.9  878.05   380.7   876.8   429.5  877.18   527.1  876.17
   605.2  873.85   673.5   872.7   741.8  872.82   849.2  867.34   881.4  864.53
   888.2   864.4   907.8  864.92   956.6  867.71   995.6  866.31  1063.8  866.78
  1141.6  874.19  1151.4  876.21  1161.1  880.12  1219.5  909.14  1297.4  950.25
#Mann= 3 , 0 , 0
       0     .06       0   881.4    .045       0   907.8     .06       0
Bank Sta=881.4,907.8
XS Rating Curve= 0 ,0
Exp/Cntr=0.3,0.1

Type RM Length L Ch R = 1 ,3155.9  ,476.7,481.7,485.8
XS GIS Cut Line= 3
     1641703.929      252677.198     1641877.876      252586.215
     1642277.066       252518.94
#Sta/Elev= 30
       0  978.25    58.9  945.04    88.3  928.24   117.8  911.71   127.6  906.38
   137.4  901.19   147.2  896.44     157  892.38   176.7  885.24   196.3  878.38
   215.6   872.5   225.2  869.07   234.9  865.81     238  865.39   244.5   864.5
   254.1   864.4   263.8   864.4   379.4   864.4   389.1  864.52   398.7  865.03
   408.4  866.15     418  868.01   427.6  870.23   437.3  872.01   446.9  873.21
   456.6  875.08   466.2  878.63   543.3  914.82   572.2  928.59   601.1  942.64
#Mann= 3 , 0 , 0
       0      .1       0     238    .045       0   263.8     .06       0
Bank Sta=238,263.8
XS Rating Curve= 0 ,0
Exp/Cntr=0.3,0.1

Type RM Length L Ch R = 1 ,2674.2  ,605.9,596.8,587.9
XS GIS Cut Line= 2
     1641799.415      252986.226     1642247.668      253000.277
#Sta/Elev= 30
       0  954.85    29.2   940.9    68.2  921.85      78  917.28    87.7  913.04
     117  900.78   126.7  896.44   136.5  891.74   165.7   876.7   175.5  871.89
   185.2  868.71     195  867.71   214.5  867.57   224.2   867.3     234   866.5
   243.7  865.22   253.5  864.51   263.2   864.4   282.7   864.4   292.5  864.53
   302.2  867.74     312  873.06   321.7  878.05   331.5  881.35   341.2  883.73
     351  887.44   360.7  892.56     390  909.13   409.5  920.21   448.5  942.62
#Mann= 3 , 0 , 0
       0      .1       0   263.2    .045       0   292.5      .1       0
Bank Sta=263.2,292.5
XS Rating Curve= 0 ,0
Exp/Cntr=0.3,0.1

Type RM Length L Ch R = 1 ,2077.5  ,244.8,240.4,235.4
XS GIS Cut Line= 2
     1641793.776      253656.506     1642250.804      253481.017
#Sta/Elev= 30
       0  976.29     9.8  970.56    39.2   953.9    68.5  937.95    97.9  922.21
   107.7  917.18   166.4  890.82   195.8  878.38   215.4  870.38   225.2  866.61
     235  864.79   244.8  864.42   253.7  864.41   254.6  864.41     284   864.5
   323.1  865.45   332.9   866.2   342.7  867.94   352.5  871.01   362.3  876.13
   372.1  882.57   381.9  888.23   391.6  891.38   401.4  893.86   411.2  897.62
     421  902.21   450.4  916.69   460.2  921.07     470  924.97   489.6  931.23
#Mann= 3 , 0 , 0
       0      .1       0     235    .045       0   254.6      .1       0
Bank Sta=235,254.6
XS Rating Curve= 0 ,0
Exp/Cntr=0.3,0.1

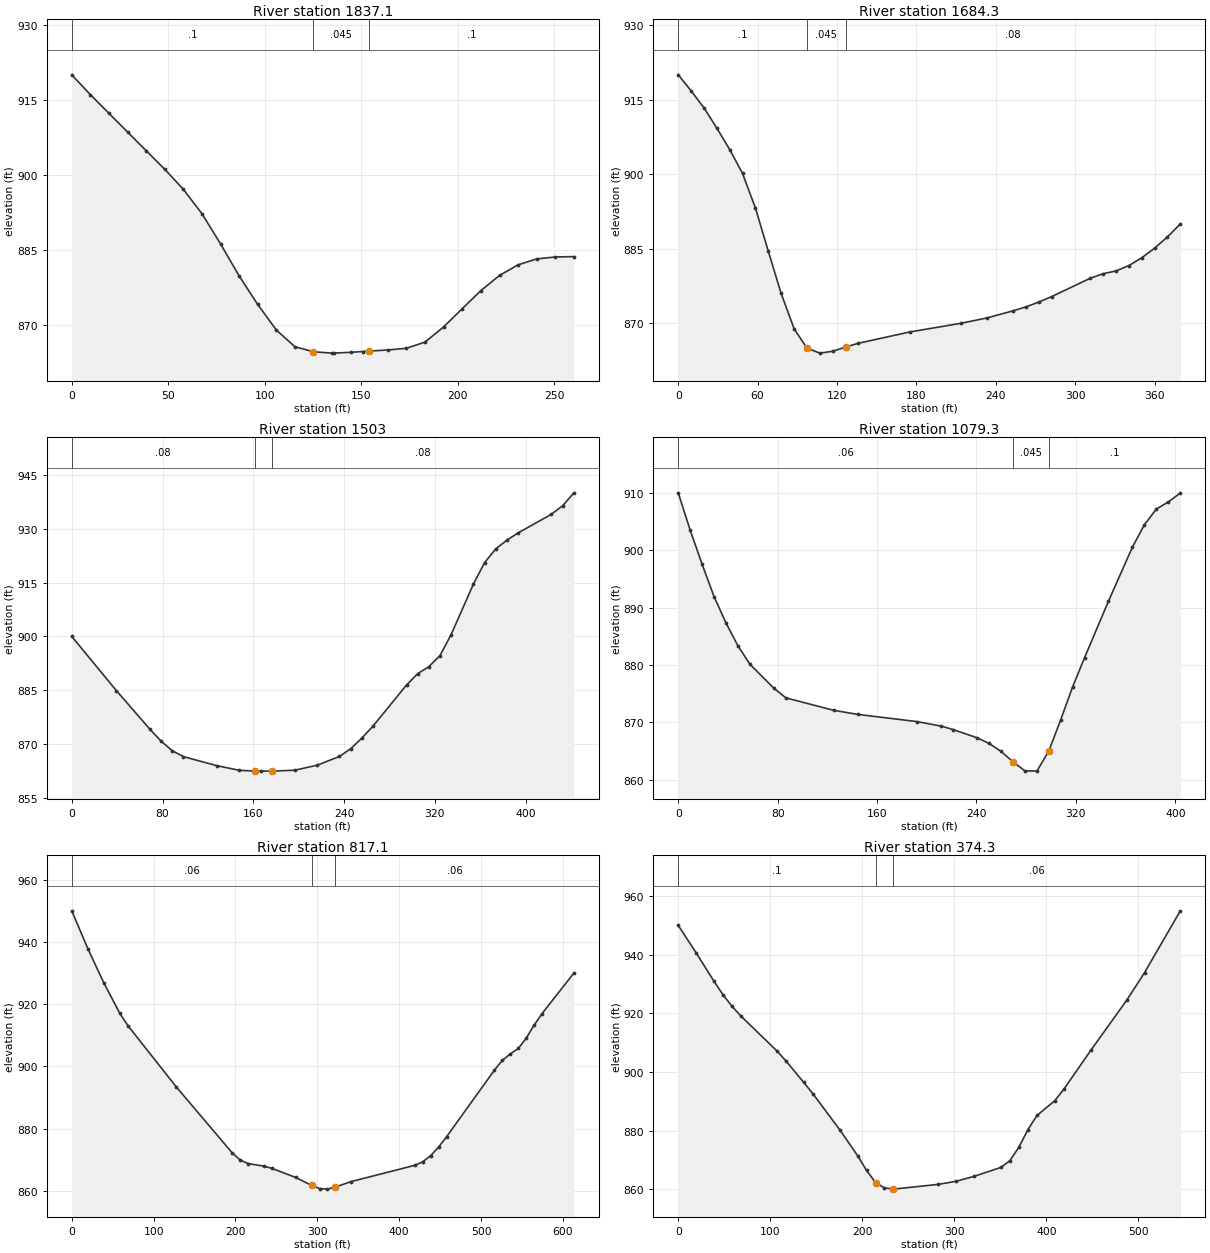
Type RM Length L Ch R = 1 ,1837.1  ,151.5,152.8,154
XS GIS Cut Line= 2
     1642034.679      253838.998     1642254.178      253699.496
#Sta/Elev= 30
       0     920     9.6  916.06    19.3  912.29    28.9  908.58    38.5  904.86
    48.2  901.12    57.8  897.14    67.4  892.29    77.1  886.22    86.7  879.84
    96.3  874.15     106  869.02   115.6   865.7   125.2  864.69   134.9  864.42
   135.7  864.43   144.5  864.58   150.7  864.74   154.1  864.83   163.8  865.05
   173.4  865.39     183  866.62   192.6  869.64   202.3   873.3   211.9   876.9
   221.6  879.94   231.2  882.05   240.8  883.23   250.4  883.62   260.1   883.7
#Mann= 3 , 0 , 0
       0      .1       0   125.2    .045       0   154.1      .1       0
Bank Sta=125.2,154.1
XS Rating Curve= 0 ,0
Exp/Cntr=0.3,0.1

Type RM Length L Ch R = 1 ,1684.3  ,164.5,181.3,198.1
XS GIS Cut Line= 2
     1642129.567      253948.923     1642459.766      253761.917
#Sta/Elev= 30
       0     920     9.7   916.8    19.5  913.33    29.2  909.28    38.9  904.96
    48.6  900.16    58.4  893.16    68.1  884.49    77.8  876.01    87.6   868.9
    97.3  865.01     107  864.01   116.8  864.39   126.5  865.23   136.2     866
   175.1  868.27   214.1  870.03   233.5   871.1     253  872.51   262.7  873.31
   272.4  874.26   282.2  875.38   311.4  879.07   321.1  879.98   330.8  880.54
   340.6  881.62   350.3  883.18     360  885.11   369.8  887.39   379.5     890
#Mann= 3 , 0 , 0
       0      .1       0    97.3    .045       0   126.5     .08       0
Bank Sta=97.3,126.5
XS Rating Curve= 0 ,0
Exp/Cntr=0.3,0.1

Type RM Length L Ch R = 1 ,1503    ,408.1,423.7,439.3
XS GIS Cut Line= 2
       1642198.2      254031.462      1642636.51      253970.053
#Sta/Elev= 30
       0     900    39.3  884.94    68.8  874.19    78.7  870.87    88.5   868.2
    98.4  866.54   127.9  864.02   147.5  862.74   161.3  862.52   167.2   862.5
   176.3   862.5   196.7  862.76   216.4  864.16     236  866.59   245.9  868.74
   255.7  871.68   265.6  875.05   295.1  886.48   304.9  889.64   314.7  891.57
   324.6  894.66   334.4  900.51   354.1  914.62   363.9  920.55   373.7  924.37
   383.6  926.82   393.4  928.82   422.9  934.05   432.8  936.42   442.6     940
#Mann= 3 , 0 , 0
       0     .08       0   161.3    .045       0   176.3     .08       0
Bank Sta=161.3,176.3
XS Rating Curve= 0 ,0
Exp/Cntr=0.3,0.1

Type RM Length L Ch R = 1 ,1079.3  ,286.3,262.2,237.3
XS GIS Cut Line= 2
      1642096.39      254109.057     1642352.621      254421.358
#Sta/Elev= 30
       0  910.03     9.6  903.52    19.2  897.58    28.8  891.94    38.5   887.3
    48.1  883.32    57.7  880.13      77  875.94    86.6  874.27     125   872.1
   144.3  871.39   192.4  870.12   211.6  869.34   221.2  868.74   240.4  867.31
   250.1  866.33   259.7  864.94   269.3  863.13   278.9  861.54   288.6  861.49
   298.2     865   307.8  870.47   317.4  876.21     327   881.3   346.2  891.13
   365.5  900.58   375.1  904.46   384.7  907.19   394.4  908.45     404     910
#Mann= 3 , 0 , 0
       0     .06       0   269.3    .045       0   298.2      .1       0
Bank Sta=269.3,298.2
XS Rating Curve= 0 ,0
Exp/Cntr=0.3,0.1

Type RM Length L Ch R = 1 ,817.1   ,453.6,442.8,428.2
XS GIS Cut Line= 3
      1641825.84      254628.049     1642009.315      254535.304
     1642410.285      254460.728
#Sta/Elev= 30
       0     950    19.6  937.86    39.2  926.84    58.7  917.06    68.5  913.15
   127.3  893.56   195.8  872.31   205.6  869.97   215.3  868.82   234.7  867.99
   244.4  867.27   273.6  864.35     293   861.8   302.7  860.78   312.4   860.6
   322.1  861.28   341.5  863.04   419.2  868.25   428.9  869.41   438.6  871.38
   448.4  874.18   458.1  877.49   516.3   898.8     526  901.96   535.7  904.02
   545.5  905.78   555.2  909.07   564.9  913.29   574.6     917   613.4     930
#Mann= 3 , 0 , 0
       0     .06       0     293    .045       0   322.1     .06       0
Bank Sta=293,322.1
XS Rating Curve= 0 ,0
Exp/Cntr=0.3,0.1

Type RM Length L Ch R = 1 ,374.3   ,222.7,217.4,211.7
XS GIS Cut Line= 2
     1642182.315      254956.586     1642576.325      254579.108
#Sta/Elev= 30
       0     950    19.5  940.64      39  930.89    48.7  926.35    58.5   922.4
    68.2  919.07   107.2  907.24   116.9  903.86   136.4  896.49   146.2  892.69
   175.4   880.4   194.9  871.54   204.6  866.52   214.4  862.37   224.1  860.52
   233.8  860.12   282.6  861.74   302.1   862.8   321.5  864.47   350.8  867.54
   360.5  869.86   370.3  874.47     380  880.39   389.8  885.22   409.2  890.26
     419  894.15   448.2  907.37   487.2  924.42   506.7  933.89   545.6  954.97
#Mann= 3 , 0 , 0
       0      .1       0   214.4    .045       0   233.8     .06       0
Bank Sta=214.4,233.8
XS Rating Curve= 0 ,0
Exp/Cntr=0.3,0.1

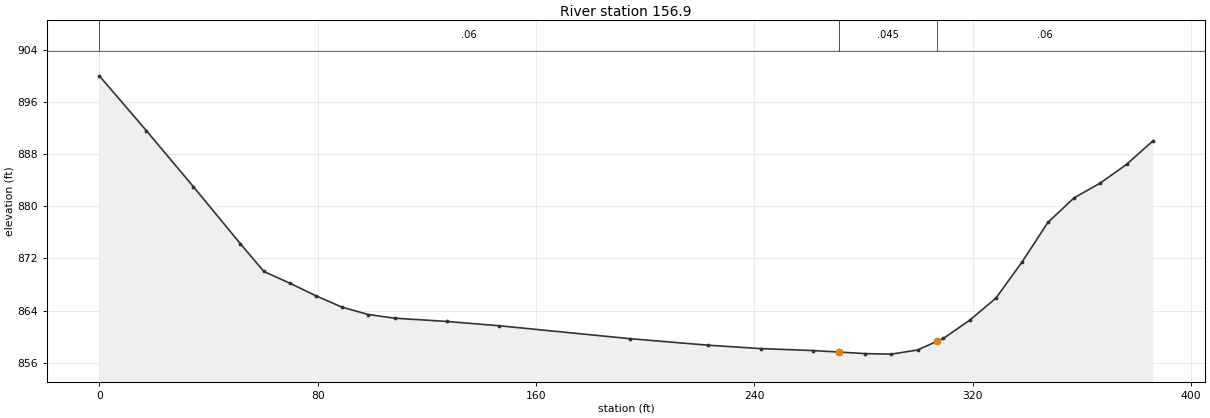
Type RM Length L Ch R = 1 ,156.9   ,163.8,156.9,149.6
XS GIS Cut Line= 3
     1642345.154      255021.745     1642405.453      255021.745
     1642578.948      254746.157
#Sta/Elev= 30
       0     900    17.2  891.61    34.5  882.98    51.7  874.25    60.3     870
    69.9  868.19    79.5  866.25      89  864.52    98.6   863.4   108.2  862.84
   127.4  862.34   146.5  861.68   194.4   859.7   223.1   858.7   242.3  858.18
   261.4  857.88     271  857.65   280.6  857.41   290.2  857.33   299.8  857.96
   307.1  859.33   309.3  859.74   318.9  862.52   328.5   865.9   338.1  871.45
   347.6  877.53   357.2   881.3   366.8  883.56   376.4  886.42     386     890
#Mann= 3 , 0 , 0
       0     .06       0     271    .045       0   307.1     .06       0
Bank Sta=271,307.1
XS Rating Curve= 0 ,0
Exp/Cntr=0.3,0.1

Chan Stop Cuts=-1
Use User Specified Reach Order=0
Composite Channel Slope=5